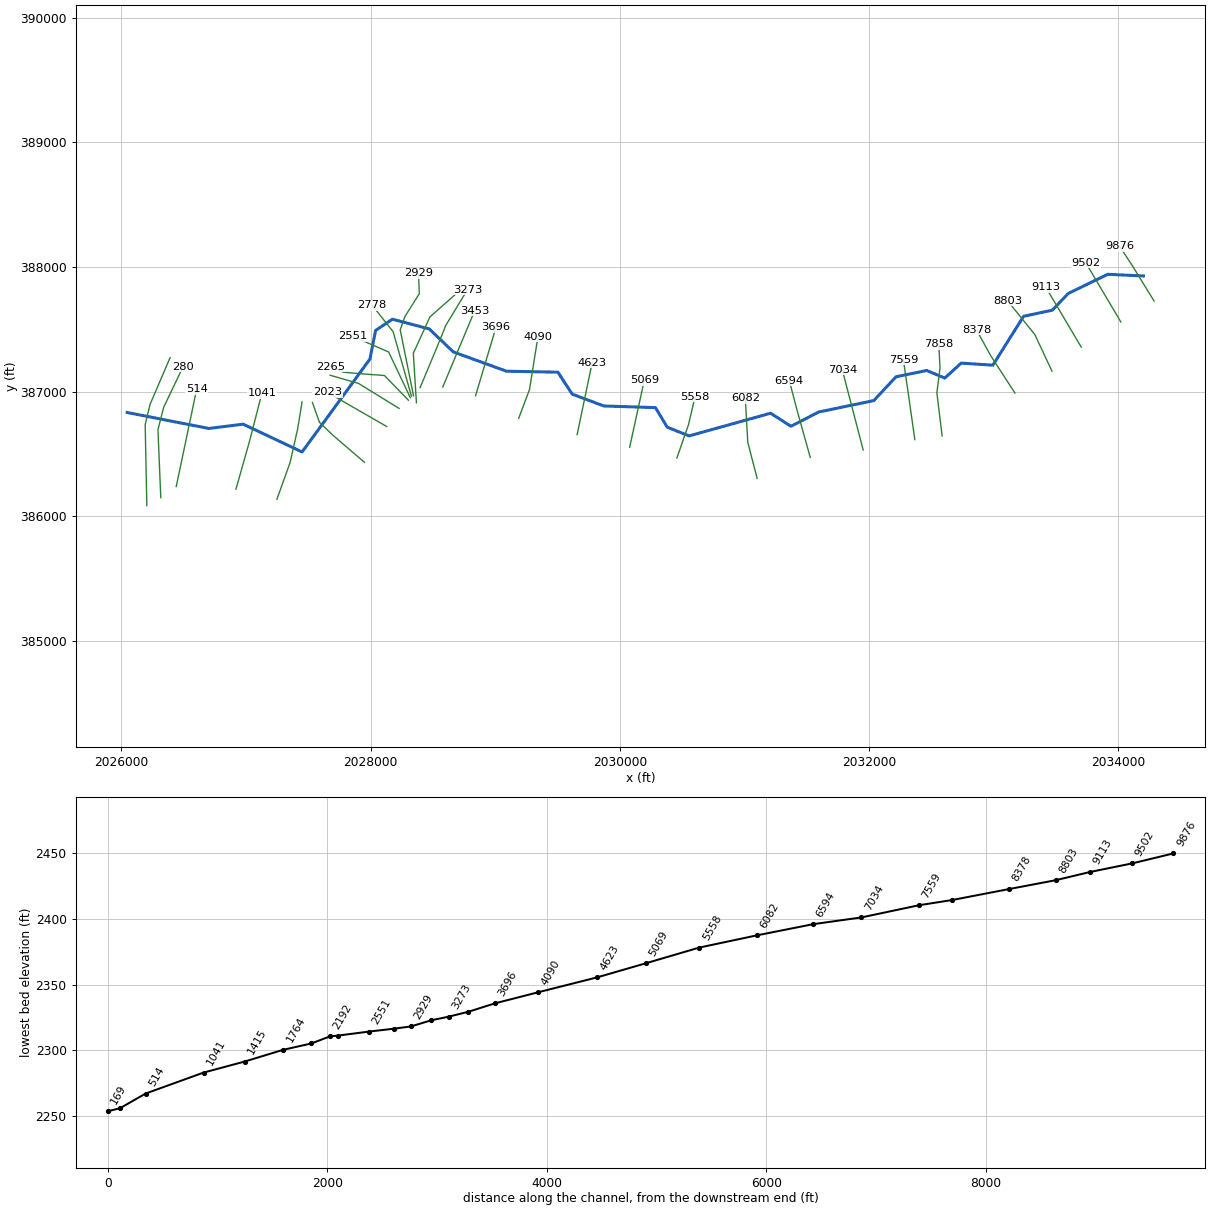
--- BURDETTECK.prj (project) ---

Proj Title=BURDETTECK
Current Plan=p01
Default Exp/Contr=0,0
English Units
Geom File=g01
Flow File=f01
Plan File=p01
BEGIN DESCRIPTION:
Stream Name- Burdette Creek
Flood Zone: Zone A
Greenbrier County, WV
County-Wide Study
WVDHSEM-2018-3, Flood Risk Project
HEC-RAS Version: 5.0.7
General Notes:
For the Hydrology Regression was used.
0.06
0.016
0.06
0.045
0.07
0.06
0.12
0.016
0.12
HECRAS 507 Rasmapper
Stream Name: BURDETTECK
Hydrology: Regression
END DESCRIPTION:
DSS Export Rating Curves= 0
DSS Export Rating Curve Sorted= 0
DSS Export Volume Flow Curves= 0
DXF Filename=..\..\..\..\..\fz_Working\Nov1\Models\BURDETTECK\BURDETTECK.
DXF OffsetX= 0
DXF OffsetY= 0
DXF ScaleX= 0
DXF ScaleY= 0

--- BURDETTECK.p01 (plan) ---

Plan Title=Floodplain
Program Version=5.07
Short Identifier=Floodplain
Geom File=g01
Flow File=f01
Subcritical Flow
K Sum by GR= 0
Std Step Tol= 0.01
Critical Tol= 0.01
Num of Std Step Trials= 20
Max Error Tol= 0.3
Flow Tol Ratio= 0.001
Split Flow NTrial= 30
Split Flow Tol= 0.02
Split Flow Ratio= 0.02
Log Output Level= 0
Friction Slope Method= 1
Unsteady Friction Slope Method= 2
Unsteady Bridges Friction Slope Method= 1
Parabolic Critical Depth
Global Vel Dist= 0 , 0 , 0
Global Log Level= 0
CheckData=True
Encroach Param=-1 ,0,0, 0
Mapping Interval=1HOUR
Computation Time Step Use Courant=        0
Computation Time Step Use Time Series=    0
Computation Time Step Count To Double=0
Computation Time Step Max Doubling=0
Computation Time Step Max Halving=0
Computation Time Step Residence Courant=0
Run HTab= 0
Run UNet= 0
Run Sediment= 0
Run PostProcess= 0
Run WQNet= 0
Run RASMapper= 0
UNET Theta= 0
UNET Theta Warmup= 0
UNET ZTol= 0
UNET ZSATol= 0
UNET MxIter= 0
UNET Max Iter WO Improvement= 0
UNET MaxInSteps= 0
UNET DtIC= 0
UNET DtMin= 0
UNET MaxCRTS= 0
UNET WFStab= 0
UNET SFStab= 0
UNET WFX= 1
UNET SFX= 1
UNET 1D Methodology=Finite Difference
UNET DSS MLevel= 1
UNET Pardiso=0
UNET DZMax Abort= 0
UNET Use Existing IB Tables= 0
UNET Froude Reduction=False
UNET Froude Limit= 0
UNET Froude Power= 0
UNET D1 Cores= 0
UNET D2 Coriolis=0
UNET D2 Cores= 0
UNET D2 Theta= 1
UNET D2 Theta Warmup= 1
UNET D2 Z Tol= 0.01
UNET D2 Volume Tol= 0.01
UNET D2 Max Iterations= 20
UNET D2 Equation= 0
UNET D2 RampUpFraction=0.1
UNET D2 TimeSlices= 1
UNET D2 BCVolumeCheck=0
UNET D1D2 MaxIter= 0
UNET D1D2 ZTol=0.01
UNET D1D2 QTol=0.1
UNET D1D2 MinQTol=1
Write IC File= 0
Write IC File at Fixed DateTime=0
Write IC File at Sim End=0
Echo Input=False
Echo Parameters=False
Echo Output=False
Write Detailed= 0
HDF Write Warmup=0
HDF Write Time Slices=0
HDF Flush=0
HDF Face Node Velocities=0
HDF Compression= 1
HDF Chunk Size= 1
HDF Spatial Parts= 1
HDF Use Max Rows=0
HDF Fixed Rows= 1
Calibration Method= 0
Calibration Iterations= 20
Calibration Max Change=0.05
Calibration Tolerance=0.2
Calibration Maximum=1.5
Calibration Minimum=0.5
Calibration Optimization Method= 1
WQ AD Non Conservative
WQ ULTIMATE=-1
WQ Max Comp Step=1HOUR
WQ Output Interval=15MIN
WQ Output Selected Increments= 0
WQ Output face flow=0
WQ Output face velocity=0
WQ Output face area=0
WQ Output face dispersion=0
WQ Output cell volume=0
WQ Output cell surface area=0
WQ Output cell continuity=0
WQ Output cumulative cell continuity=0
WQ Output face conc=0
WQ Output face dconc_dx=0
WQ Output face courant=0
WQ Output face peclet=0
WQ Output face adv mass=0
WQ Output face disp mass=0
WQ Output cell mass=0
WQ Output cell source sink temp=0
WQ Output nsm pathways=0
WQ Output nsm derived pathways=0
WQ Output MaxMinRange=-1
WQ Daily Max Min Mean=-1
WQ Daily Range=0
WQ Daily Time=0
WQ Create Restart=0
WQ Fixed Restart=0
WQ System Summary=0
WQ Write To DSS=0
WQ Use Fixed Temperature=0
Sorting and Armoring Iterations= 10
XS Update Threshold= 0.02
Bed Roughness Predictor= 0
Hydraulics Update Threshold= 0.02
Energy Slope Method= 1
Volume Change Method= 1
Sediment Retention Method= 0
XS Weighting Method= 0
Number of US Weighted Cross Sections= 1
Number of DS Weighted Cross Sections= 1
Upstream XS Weight=0
Main XS Weight=1
Downstream XS Weight=0
Number of DS XS's Weighted with US Boundary= 1
Upstream Boundary Weight= 1
Weight of XSs Associated with US Boundary= 0
Number of US XS's Weighted with DS Boundary= 1
Downstream Boundary Weight= 0.5
Weight of XSs Associated with DS Boundary= 0.5
Percentile Method= 0
Sediment Output Level= 3
Mass or Volume Output= 0
Output Increment Type= 1
Profile and TS Output Increment= 1
XS Output Flag= 0
XS Output Increment= 10
Write Gradation File= 0
Read Gradation Hotstart= 0
Write HDF5 File= 1
Write Binary Output= 1
Write DSS Sediment File= 0
SV Curve= 0
Specific Gage Flag= 0

--- BURDETTECK.f01 (steady flow) ---

Flow Title=NFF Regression Equation
Program Version=5.07
Number of Profiles= 6
Profile Names=f1p,f10p,f4p,f2p,f02p,f1pplus
River Rch & RM=BURDETTECK,Main            ,9876
     547     289     384     463     765     810
River Rch & RM=BURDETTECK,Main            ,7858
     846     454     599     718    1170    1250
River Rch & RM=BURDETTECK,Main            ,2192
    1200     653     857    1020    1650    1780
Boundary for River Rch & Prof#=BURDETTECK,Main            , 1
Up Type= 0
Dn Type= 3
Dn Slope=0.0205
Boundary for River Rch & Prof#=BURDETTECK,Main            , 2
Up Type= 0
Dn Type= 3
Dn Slope=0.0205
Boundary for River Rch & Prof#=BURDETTECK,Main            , 3
Up Type= 0
Dn Type= 3
Dn Slope=0.0205
Boundary for River Rch & Prof#=BURDETTECK,Main            , 4
Up Type= 0
Dn Type= 3
Dn Slope=0.0205
Boundary for River Rch & Prof#=BURDETTECK,Main            , 5
Up Type= 0
Dn Type= 3
Dn Slope=0.0205
Boundary for River Rch & Prof#=BURDETTECK,Main            , 6
Up Type= 0
Dn Type= 3
Dn Slope=0.0205
DSS Import GetInterval= 0
DSS Import GetPeak= 0
DSS Import FillOption= 0

--- BURDETTECK.g01 (geometry) ---

Geom Title=USGS 10m DEM
Program Version=5.07

River Reach=BURDETTECK      ,Main
Reach XY= 30
    2034200.9009387928.361199999    2033914.8326387941.560900001
    2033597.6231     387787.5066    2033471.1794     387654.0601
    2033239.7695387604.452099999    2032993.1173387212.275900001
    2032738.7367387228.998299999    2032607.5496387108.936000001
    2032462.1081387169.818600001    2032216.0195387119.163699999
    2032037.8191     386928.1228    2031596.8787      386836.952
    2031373.2909      386722.215    2031209.4461386826.701300001
    2030556.2846     386644.9386    2030380.4617386714.846100001
    2030285.8808     386871.7501    2029871.3494386884.998400001
     2029617.986386980.093599999    2029502.6727     387156.1842
    2029090.1532     387163.9486    2028663.5101387318.820800001
    2028470.8561387503.168199999    2028174.5457     387581.2281
    2028040.2446387491.001700001    2027995.1161387262.139900001
    2027450.3098     386515.9046    2026977.7619386738.819499999
    2026701.2516386704.5938000012026046.53965834386832.746139384

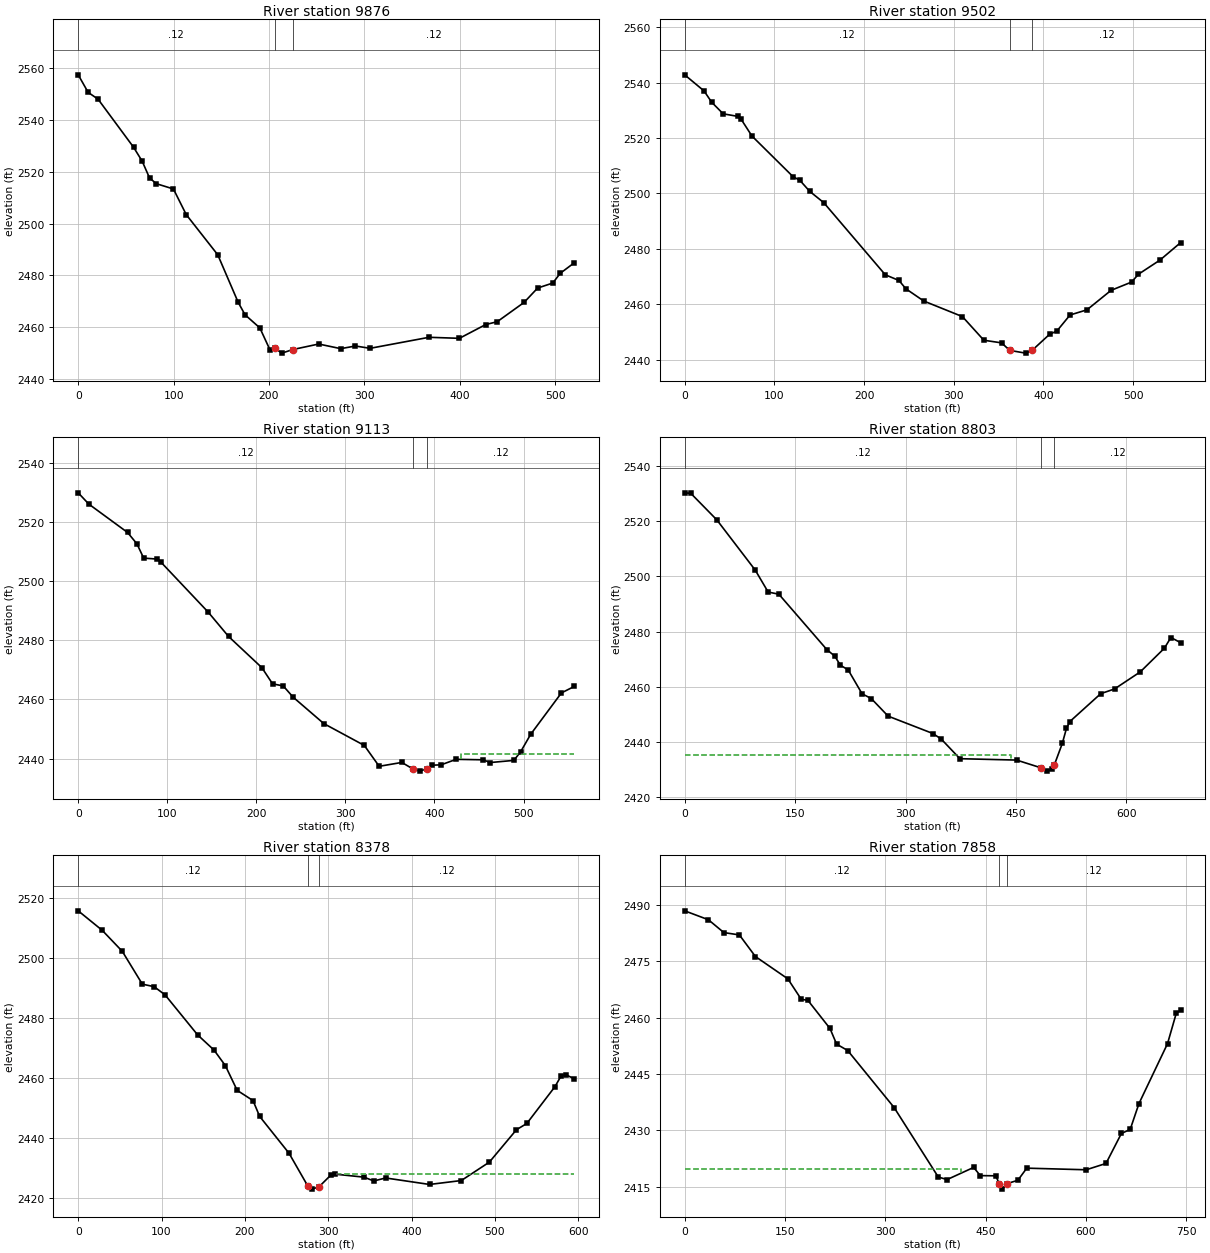
Type RM Length L Ch R = 1 ,9876    ,368.8,373.7,372.1
XS GIS Cut Line= 3
2034286.75426073 387727.638186592034111.77971076388011.334787022
2034009.85278845388167.622734565
#Sta/Elev= 30
       0 2557.49    10.4 2550.71    20.8 2548.08    58.1 2529.46      67 2524.14
    74.8 2517.62    81.9 2515.41    99.8 2513.37   113.3 2503.43   146.3 2487.92
   167.7 2469.55   174.9 2464.74   190.4 2459.67   201.1 2451.13   205.8 2451.88
   213.5 2449.92   224.8 2451.29   252.1 2453.44   275.2 2451.65   290.6 2452.67
     306 2451.78   367.8 2456.04   399.6 2455.64   427.2 2460.97   439.2 2462.05
   467.4 2469.52   481.6 2475.07   497.5 2477.01   505.3 2480.77   519.9  2484.8
#Mann= 3 ,-1 , 0
       0     .12       0   205.8     .04       0   224.8     .12       0
Bank Sta=205.8,224.8
XS Rating Curve= 0 ,0
Exp/Cntr(USF)=0,0
Exp/Cntr=0.3,0.1

Type RM Length L Ch R = 1 ,9502    ,388.1,389,387.5
XS GIS Cut Line= 2
2034020.04548068387559.4587647772033738.04766229388035.117735561
#Sta/Elev= 30
       0  2542.8    21.6 2536.99    30.1 2532.92    42.9 2528.73    59.7 2527.78
      63 2526.74      75 2520.72   120.7 2506.09   128.4 2504.74   139.4 2500.76
   155.1 2496.66   223.7 2470.64     239 2468.58   246.6  2465.6   266.6 2461.17
   309.7 2455.55   333.6 2447.02   353.4 2446.07   362.4 2443.36   380.1 2442.37
   387.7 2443.45   406.8 2449.14     415 2450.34   429.7 2456.13   448.6    2458
   475.4 2465.02   498.3 2468.01     506 2470.85     530 2475.95     553 2482.25
#Mann= 3 ,-1 , 0
       0     .12       0   362.4     .04       0   387.7     .12       0
Bank Sta=362.4,387.7
XS Rating Curve= 0 ,0
Exp/Cntr(USF)=0,0
Exp/Cntr=0.3,0.1

Type RM Length L Ch R = 1 ,9113    ,307.2,309.7,309.8
XS GIS Cut Line= 2
2033702.37323948387357.3037021932033418.67663905387836.360237055
#Sta/Elev= 30
       0 2529.88    11.9 2526.07    55.4 2516.47    65.9 2512.63    73.5 2507.79
    88.7 2507.47    92.5 2506.55   145.9 2489.53   168.8 2481.29   206.2 2470.73
   218.2 2465.26   230.2 2464.55   241.3 2460.75   275.7 2451.82   321.2 2444.42
   337.9 2437.36   363.3 2438.67   376.3 2436.38   383.4 2435.73   391.8 2436.54
   397.6 2437.74   407.4 2437.86   424.3 2439.72   454.8 2439.56   462.4 2438.63
   489.1 2439.36   496.7 2442.27     508 2448.19   542.5 2462.19   556.8 2464.36
#Mann= 3 ,-1 , 0
       0     .12       0   376.3     .04       0   391.8     .12       0
#XS Ineff= 2 , 0
                          429.54         2441.41
Permanent Ineff=
       F       F
Bank Sta=376.3,391.8
XS Rating Curve= 0 ,0
Exp/Cntr(USF)=0,0
Exp/Cntr=0.3,0.1

Type RM Length L Ch R = 1 ,8803    ,425.6,425,426.3
XS GIS Cut Line= 3
2033467.94131816387163.6425498022033330.33997304387457.531842466
2033111.19709007387729.336968628
#Sta/Elev= 30
       0 2530.25     8.3 2530.07    43.7 2520.45    95.9 2502.26   113.4 2494.34
   127.9 2493.57   193.1 2473.52     204 2471.12   211.4 2467.89   222.1 2466.16
     241 2457.51   253.4 2455.81   276.4 2449.43   337.3 2443.13   348.6 2441.11
   373.9 2434.03   450.9 2433.53   483.7 2430.76   491.9 2429.53   499.4 2430.14
   502.2 2431.81     513 2439.58   518.6 2444.98   523.2 2447.46   565.2 2457.57
   583.9 2459.26   618.9 2465.45   651.6    2474   660.5 2477.89   673.7 2476.02
#Mann= 3 ,-1 , 0
       0     .12       0   483.7     .04       0   502.2     .12       0
#XS Ineff= 2 , 0
          443.54 2435.38
Permanent Ineff=
       F       F
Bank Sta=483.7,502.2
XS Rating Curve= 0 ,0
Exp/Cntr(USF)=0,0
Exp/Cntr=0.3,0.1

Type RM Length L Ch R = 1 ,8378    ,523.4,520.4,514.8
XS GIS Cut Line= 3
2033170.65446142386988.6679998352032975.29452699387289.352420653
2032861.47613041387496.603829352
#Sta/Elev= 30
       0 2515.58    28.8 2509.08    52.9 2502.07    76.9 2491.14    91.1 2490.29
   104.2 2487.56   143.3 2474.21   162.9 2469.17   176.5 2463.99   190.7 2455.73
   209.7 2452.32   217.7 2447.04   252.9 2434.77   275.7 2423.71   280.3  2422.8
   288.8 2423.55   303.7 2427.65   307.6 2427.81   342.9 2426.79   354.6 2425.52
   368.8 2426.52   421.5 2424.36   459.6 2425.66   493.3 2431.81   525.8 2442.61
   538.2 2444.68   571.9 2456.93   579.4 2460.56   585.1 2460.93     595  2459.6
#Mann= 3 ,-1 , 0
       0     .12       0   275.7     .04       0   288.8     .12       0
#XS Ineff= 2 , 0
                          309.35         2427.96
Permanent Ineff=
       F       F
Bank Sta=275.7,288.8
XS Rating Curve= 0 ,0
Exp/Cntr(USF)=0,0
Exp/Cntr=0.3,0.1

Type RM Length L Ch R = 1 ,7858    ,291,298.3,296
XS GIS Cut Line= 4
2032586.27344017386643.8152460172032543.80388921386990.366781874
2032569.28561979387190.8230624192032559.09292756387381.086650733
#Sta/Elev= 30
       0 2488.35    35.5 2485.98    58.6 2482.57    81.8 2481.95   105.8 2476.21
   154.3 2470.28   174.3 2464.86   184.3 2464.56   217.3  2457.1   227.2 2452.94
   243.8 2451.24   313.2  2436.1   379.3 2417.63   392.5 2416.96   432.2 2420.19
   442.1 2418.01   465.3 2417.96   470.6 2415.78   475.2 2414.42   482.4  2415.9
   498.3 2416.77   511.6 2419.99   600.5 2419.56   630.1 2421.24   653.1  2429.2
   666.3 2430.29   679.4 2437.15   722.1 2453.06   735.3 2461.21   741.7 2461.89
#Mann= 3 ,-1 , 0
       0     .12       0   470.6     .04       0   482.4     .12       0
#XS Ineff= 2 , 0
          412.89 2419.85
Permanent Ineff=
       F       F
Bank Sta=470.6,482.4
XS Rating Curve= 0 ,0
Exp/Cntr(USF)=0,0
Exp/Cntr=0.3,0.1

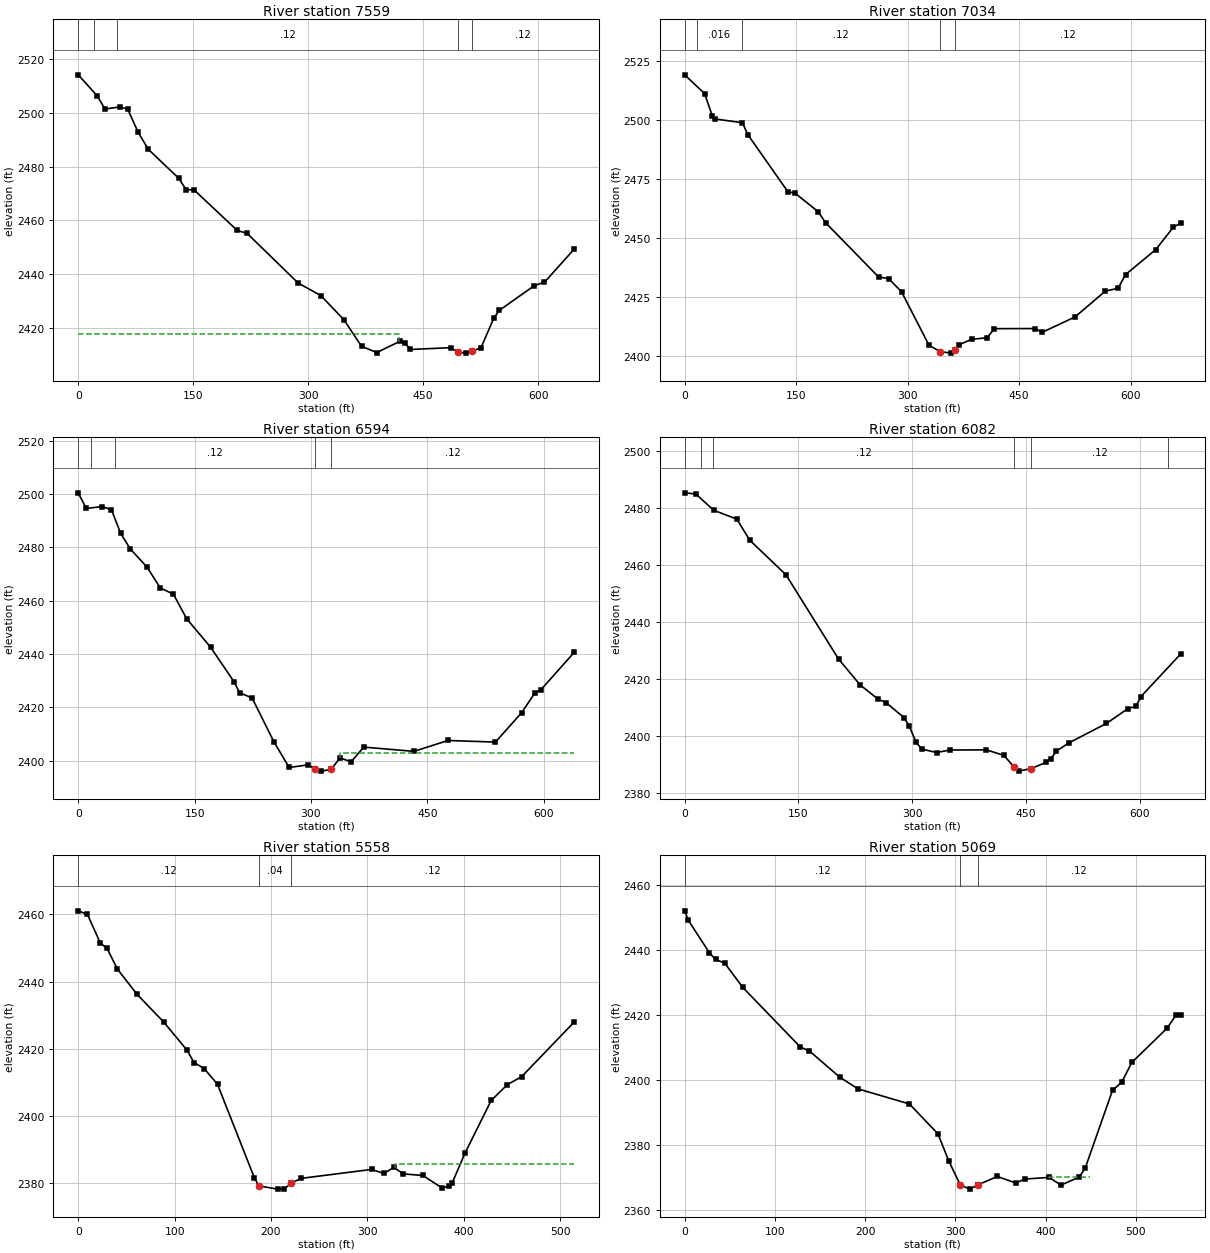
Type RM Length L Ch R = 1 ,7559    ,520.9,525.7,522.2
XS GIS Cut Line= 3
 2032367.1305572386614.9359513622032317.86587809386961.487487219
2032275.39632712387255.376779882
#Sta/Elev= 30
       0 2514.23      25 2506.32    34.9 2501.48    54.8  2502.3    64.8 2501.32
      78 2492.92    91.3 2486.51     131 2475.71     141 2471.37   150.9 2471.42
   207.3 2456.27   220.5 2455.11   286.8 2436.67   316.6 2431.96   346.5 2422.99
   369.6 2413.07   389.5 2410.74   419.4 2414.89     426 2414.36   433.3 2411.88
   485.7 2412.55   495.6 2410.88   505.6 2410.52   513.22411.205   525.5 2412.54
     542 2423.47   549.2 2426.42   595.1 2435.68   608.3 2436.95     647 2449.26
#Mann= 5 ,-1 , 0
       0     .12       0   21.18    .016       0   51.01     .12       0
   495.6     .04       0   513.2     .12       0
#XS Ineff= 2 , 0
          418.79 2417.57
Permanent Ineff=
       F       F
Bank Sta=495.6,513.2
XS Rating Curve= 0 ,0
Exp/Cntr(USF)=0,0
Exp/Cntr=0.3,0.1

Type RM Length L Ch R = 1 ,7034    ,439.1,439.8,438.8
XS GIS Cut Line= 2
2031952.62773981386531.6956314752031784.44831799387177.232806111
#Sta/Elev= 30
       0 2519.16    26.8 2511.21      37  2501.9    40.4 2500.48    77.7 2498.86
    84.9 2493.84   138.7 2469.68   148.9 2468.91   179.4 2461.19   189.6 2456.47
   260.8  2433.5   274.3 2432.82   291.7 2427.22   328.6 2404.59   343.42401.897
   358.2 2401.22     364 2402.47   369.3 2404.79   386.2 2407.09   406.6 2407.71
   416.7 2411.59     471 2411.63   481.2 2410.08   525.2 2416.58   565.9 2427.54
   582.9 2428.67     593 2434.49   633.7 2445.12   657.4 2454.62   667.1  2456.3
#Mann= 5 ,-1 , 0
       0     .12       0   16.12    .016       0   77.16     .12       0
   343.4     .04       0     364     .12       0
Bank Sta=343.4,364
XS Rating Curve= 0 ,0
Exp/Cntr(USF)=0,0
Exp/Cntr=0.3,0.1

Type RM Length L Ch R = 1 ,6594    ,509.2,511.5,506.4
XS GIS Cut Line= 3
2031527.93223018386472.2382601272031419.21017971386861.259346947
2031359.75280836387088.896140108
#Sta/Elev= 30
       0 2500.44    10.4 2494.59    30.8 2495.27    42.9  2494.1    54.6 2485.33
    66.9 2479.48    88.7 2472.59   105.7 2464.84   122.8 2462.38   139.8 2453.22
   170.5 2442.59   201.1 2429.48   207.9 2425.45     224 2423.57   252.2  2407.1
   271.9 2397.45   296.5 2398.44   305.6 2396.73   313.5 2396.08   326.1 2396.77
   337.4 2401.04   351.8 2399.58     368 2405.09   432.6 2403.49   476.7 2407.57
   537.8 2406.97   571.7 2418.06   588.6  2425.4   595.9 2426.45   639.2 2440.59
#Mann= 5 ,-1 , 0
       0     .12       0   16.59    .016       0   47.26     .12       0
   305.6     .04       0   326.1     .12       0
#XS Ineff= 2 , 0
                          336.97          2402.7
Permanent Ineff=
       F       F
Bank Sta=305.6,326.1
XS Rating Curve= 0 ,0
Exp/Cntr(USF)=0,0
Exp/Cntr=0.3,0.1

Type RM Length L Ch R = 1 ,6082    ,529.8,524.5,514.6
XS GIS Cut Line= 3
2031101.53793851386304.0588383142031026.79152882386592.851784861
2031006.40614435386947.897230911
#Sta/Elev= 30
       0 2485.26    14.6 2484.87    38.3 2479.14    68.8 2476.02    85.7 2468.66
   133.5 2456.51     203 2426.89   231.5 2417.81   255.2 2412.82   265.4 2411.68
   289.1 2406.41   295.9 2403.53   305.1 2397.75   312.6 2395.34   332.1 2394.13
   349.9 2395.01   397.8 2395.06   420.8 2393.14   434.1 2389.13   440.5  2387.6
     457 2388.51   476.7 2390.68   483.3 2392.03   489.8 2394.56   506.3 2397.48
   556.1 2404.33     584 2409.47     595 2410.37   601.6 2413.77   653.9 2428.69
#Mann= 6 ,-1 , 0
       0    .016       0   21.82     .06       0   37.67     .12       0
   434.1     .04       0     457     .12       0  637.28     .06       0
Bank Sta=434.1,457
XS Rating Curve= 0 ,0
Exp/Cntr(USF)=0,0
Exp/Cntr=0.3,0.1

Type RM Length L Ch R = 1 ,5558    ,487.9,489,485.3
XS GIS Cut Line= 3
2030457.69954591386467.1419140112030551.13255803386735.549476097
2030603.79480123386959.788705181
#Sta/Elev= 30
       0 2461.02     9.6 2459.96    22.9 2451.45    29.9 2449.89    40.5 2443.76
    61.1 2436.19    88.9  2427.9   112.7 2419.66   120.2 2415.94   130.6 2414.16
   144.5 2409.47   182.7  2381.7   187.4 2379.27     207 2378.31     214 2378.43
   220.9 2380.07   231.3 2381.51   304.5 2384.17   317.2 2382.97   327.3 2384.76
   337.4 2382.83   357.6 2382.37   377.8 2378.59   384.6 2379.28   387.9 2380.12
   401.4 2389.09   428.4 2404.65   445.2 2409.36   460.1 2411.76   514.5 2427.95
#Mann= 3 ,-1 , 0
       0     .12       0   187.4     .04       0   220.9     .12       0
#XS Ineff= 2 , 0
                          328.83         2385.68
Permanent Ineff=
       F       F
Bank Sta=187.4,220.9
XS Rating Curve= 0 ,0
Exp/Cntr(USF)=0,0
Exp/Cntr=0.3,0.1

Type RM Length L Ch R = 1 ,5069    ,445.6,445.9,445.5
XS GIS Cut Line= 2
2030078.87115132386553.7797979752030196.08711198387090.594922146
#Sta/Elev= 30
       0 2452.03       4 2449.13    27.5 2439.06    34.2 2437.05    44.3 2435.94
    64.4 2428.43   128.2 2410.07   138.3 2408.84   171.9 2400.78     192 2397.19
   249.1 2392.53   280.6 2383.33   292.8 2374.87   305.4 2367.59   316.1 2366.31
   324.7  2367.6   324.7 2367.62   346.5 2370.21   366.7  2368.2     377 2369.41
   403.6 2369.92     417 2367.56   437.2 2370.02   443.9 2372.88   474.1 2396.79
   484.2 2399.22   495.5 2405.35   534.6  2415.9   544.6 2420.03   549.5 2420.01
#Mann= 3 ,-1 , 0
       0     .12       0   305.4     .04       0   324.7     .12       0
#XS Ineff= 1 ,-1
  404.04  448.66 2369.98
Permanent Ineff=
       F
Bank Sta=305.4,324.7
XS Rating Curve= 0 ,0
Exp/Cntr(USF)=0,0
Exp/Cntr=0.3,0.1

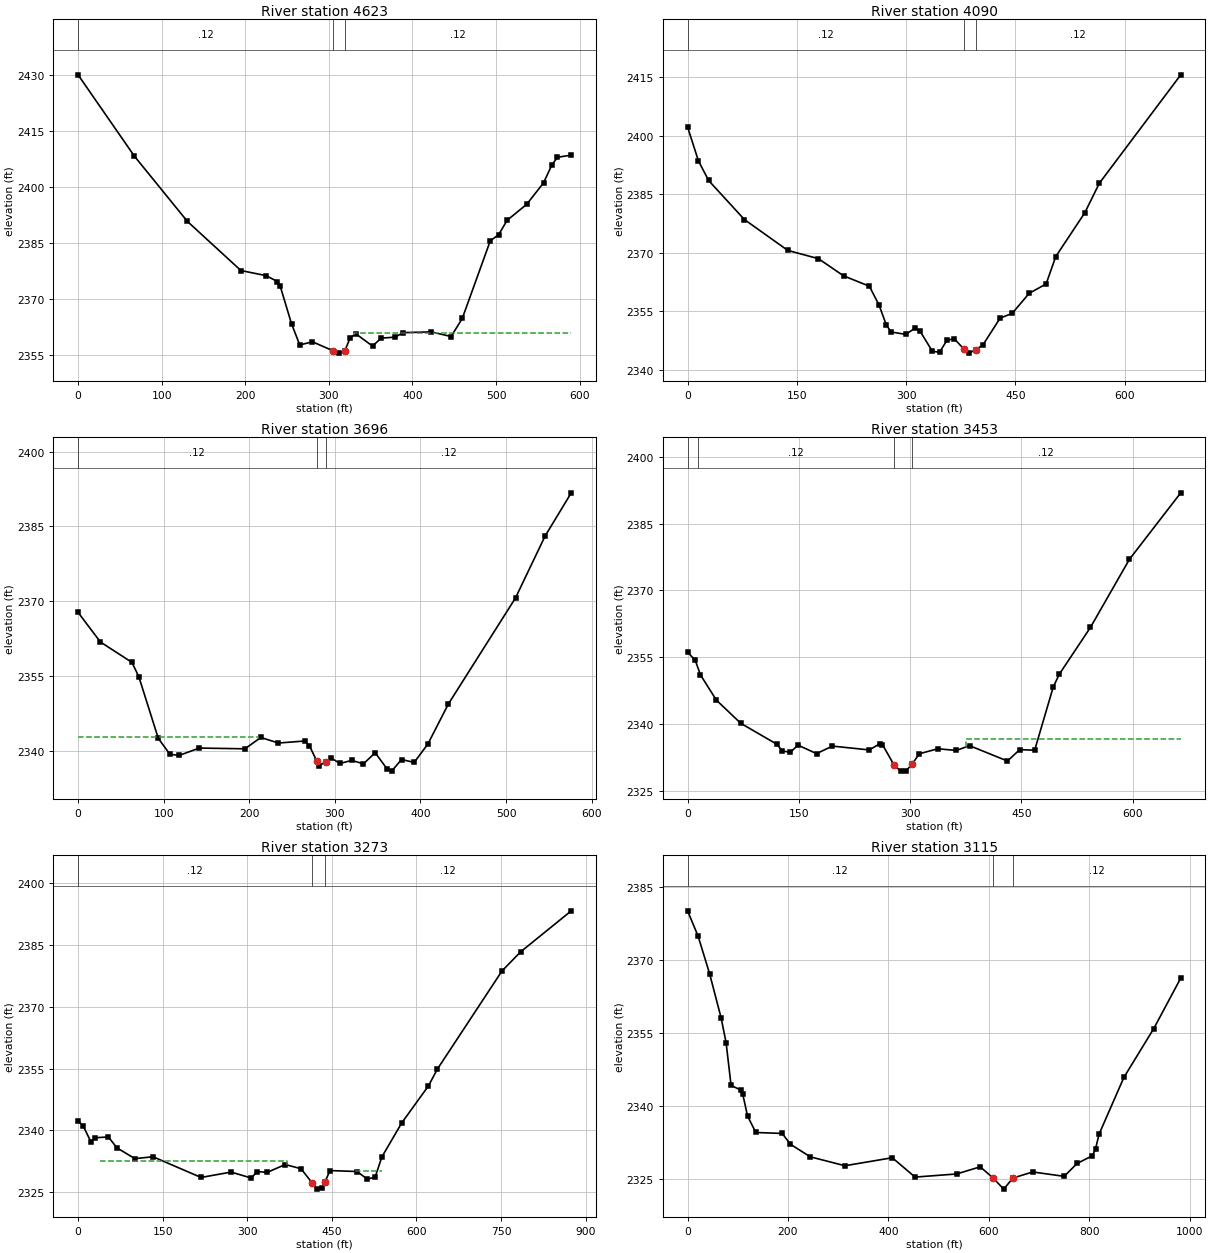
Type RM Length L Ch R = 1 ,4623    ,531.4,533.3,532.1
XS GIS Cut Line= 2
2029657.57320577386655.7067202862029778.18673051387233.292613382
#Sta/Elev= 30
       0 2429.94    67.4 2408.19   130.7 2390.77   194.8 2377.62     225 2376.25
   238.4 2374.68   241.7 2373.52   255.4 2363.35   265.2 2357.73   280.4 2358.57
   305.5 2356.12   312.1 2355.54   319.2  2356.2   325.5 2359.63   332.2 2360.72
   352.3 2357.42   362.4 2359.53   379.1 2359.82   389.2 2361.03   422.7 2361.21
   446.2 2359.98   459.6  2364.8   493.1 2385.56   503.1  2387.2   513.2 2391.04
   536.7 2395.33   556.8 2401.05   566.8 2405.85   573.5  2407.9     590 2408.48
#Mann= 3 ,-1 , 0
       0     .12       0   305.5     .04       0   319.2     .12       0
#XS Ineff= 2 , 0
                          330.36         2360.85
Permanent Ineff=
       F       F
Bank Sta=305.5,319.2
XS Rating Curve= 0 ,0
Exp/Cntr(USF)=0,0
Exp/Cntr=0.3,0.1

Type RM Length L Ch R = 1 ,4090    ,394.1,393.9,391.5
XS GIS Cut Line= 4
2029188.70936314386786.5129372522029275.34724711 387017.54729449
2029311.02166991387241.7865235742029343.29852865387442.242804119
#Sta/Elev= 30
       0  2402.2    14.9 2393.52    28.9 2388.49      78 2378.49   137.5 2370.59
   179.6 2368.47   214.2 2364.07   249.5 2361.42   262.8 2356.58   272.8 2351.47
   279.4  2349.7   299.3 2349.09   312.6 2350.73   319.3 2349.84   335.9 2344.77
   345.8 2344.51   355.8 2347.53   365.8    2348   379.6 2345.26   385.7 2344.29
   395.7 2345.16   405.6 2346.47   428.9 2353.25   445.5 2354.47   468.8  2359.6
     492    2362   505.3 2369.02   545.2 2380.25   565.1 2387.79   676.8 2415.54
#Mann= 3 ,-1 , 0
       0     .12       0   379.6     .04       0   395.7     .12       0
Bank Sta=379.6,395.7
XS Rating Curve= 0 ,0
Exp/Cntr(USF)=0,0
Exp/Cntr=0.3,0.1

Type RM Length L Ch R = 1 ,3696    ,244.1,242.7,241.4
XS GIS Cut Line= 2
2028842.15782728386966.5838333352029006.93968502387518.687995852
#Sta/Elev= 30
       0 2367.72    26.1 2361.78    62.9 2357.69      71 2354.79    93.7 2342.44
   107.4 2339.22   118.4 2339.03   141.6 2340.49   194.9 2340.34   213.5 2342.61
   234.1  2341.5   264.9 2341.91   270.2    2341   278.6 2337.96     282 2336.97
   289.8 2337.79   295.7 2338.48     306  2337.4   319.7 2338.01   333.4 2337.33
   347.1 2339.55     361 2336.31   366.3 2335.86   377.9 2338.19   392.7 2337.61
   408.7 2341.31   432.6 2349.33   511.1 2370.64   545.6 2383.04   576.2 2391.72
#Mann= 3 ,-1 , 0
       0     .12       0   278.6     .04       0   289.8     .12       0
#XS Ineff= 2 , 0
          210.29 2342.66
Permanent Ineff=
       F       F
Bank Sta=278.6,289.8
XS Rating Curve= 0 ,0
Exp/Cntr(USF)=0,0
Exp/Cntr=0.3,0.1

Type RM Length L Ch R = 1 ,3453    ,183.3,180.6,183.1
XS GIS Cut Line= 2
 2028579.0580153387037.0002363672028835.76285668387650.449305831
#Sta/Elev= 30
       0 2356.15    10.3 2354.34    17.4 2351.05    38.8 2345.39    71.8 2340.17
   120.6 2335.46   127.7 2333.98   138.4 2333.66     149 2335.27   173.9 2333.37
   195.3 2335.06     245  2334.2   259.3 2335.59   262.8 2335.39   278.3 2330.85
   287.4 2329.44     295 2329.57   302.5 2330.94   312.5 2333.34   337.5 2334.46
   362.4 2334.08   380.2 2335.16   431.3 2331.71   447.9 2334.27     468 2334.13
     493 2348.29   501.1 2351.16   543.2  2361.7   595.8    2377     665 2391.92
#Mann= 4 ,-1 , 0
       0    .016       0   13.44     .12       0   278.3     .04       0
   302.5     .12       0
#XS Ineff= 2 , 0
          258.39 2335.48  375.52         2336.71
Permanent Ineff=
       F       F
Bank Sta=278.3,302.5
XS Rating Curve= 0 ,0
Exp/Cntr(USF)=0,0
Exp/Cntr=0.3,0.1

Type RM Length L Ch R = 1 ,3273    ,192.7,157.1,186.5
XS GIS Cut Line= 4
2028397.46750379387032.1506518252028532.36748693387356.205002391
2028604.51291109387533.6299202552028776.96034462387817.496183816
#Sta/Elev= 30
       02342.209   8.7112341.144  22.6692337.215  29.7772338.168  53.8772338.366
  68.932 2335.71 100.8522333.099 132.8362333.556 218.1262328.526 271.4322329.832
 307.3072328.372 317.344 2329.97   335.42329.756 367.3282331.665 395.2812330.652
   415.42327.168 423.9952325.688 433.0492325.958   438.22327.501 446.6062330.199
 494.8292329.971 512.5382328.147 526.7042328.549   538.8 2333.52 574.0462341.789
 621.3452350.768 637.2362354.856 751.8642378.716 784.9622383.365 874.6862393.323
#Mann= 3 ,-1 , 0
       0     .12       0   415.4     .04       0   438.2     .12       0
#XS Ineff= 2 ,-1
   39.01  371.012332.504  491.39  538.96  2330.1
Permanent Ineff=
       F       F
Bank Sta=415.4,438.2
XS Rating Curve= 0 ,0
Exp/Cntr(USF)=0,0
Exp/Cntr=0.3,0.1

Type RM Length L Ch R = 1 ,3115    ,150.9,186.8,153.4
XS GIS Cut Line= 4
2028367.80269287386910.7896250612028342.90484987387307.796772913
2028476.25086737387599.606311129 2028674.0760662387774.350371967
#Sta/Elev= 30
       0 2380.19  20.9392375.002  43.8562367.286  66.9612358.132  76.823 2353.05
  86.6852344.292 106.4092343.318 109.6962342.614 119.5582337.985 135.9942334.613
 188.5912334.417 205.0272332.189 244.4742329.613 313.5072327.778 407.9022329.424
 453.1992325.443 536.1642326.088 583.0572327.555 608.3072325.295  629.952322.969
 648.2052325.249 687.664  2326.5 750.4272325.595 775.8762328.241 806.5192329.833
 812.7512331.216 819.724 2334.24 869.3632345.957 928.8322355.985 982.5722366.368
#Mann= 3 , 0 , 0
       0     .12       0 608.307     .04       0 648.205     .12       0
#XS Ineff= 2 , 0
          562.36 2326.71
Permanent Ineff=
       F       F
Bank Sta=608.307,648.205
XS Rating Curve= 0 ,0
Exp/Cntr(USF)=0,0
Exp/Cntr=0.3,0.1

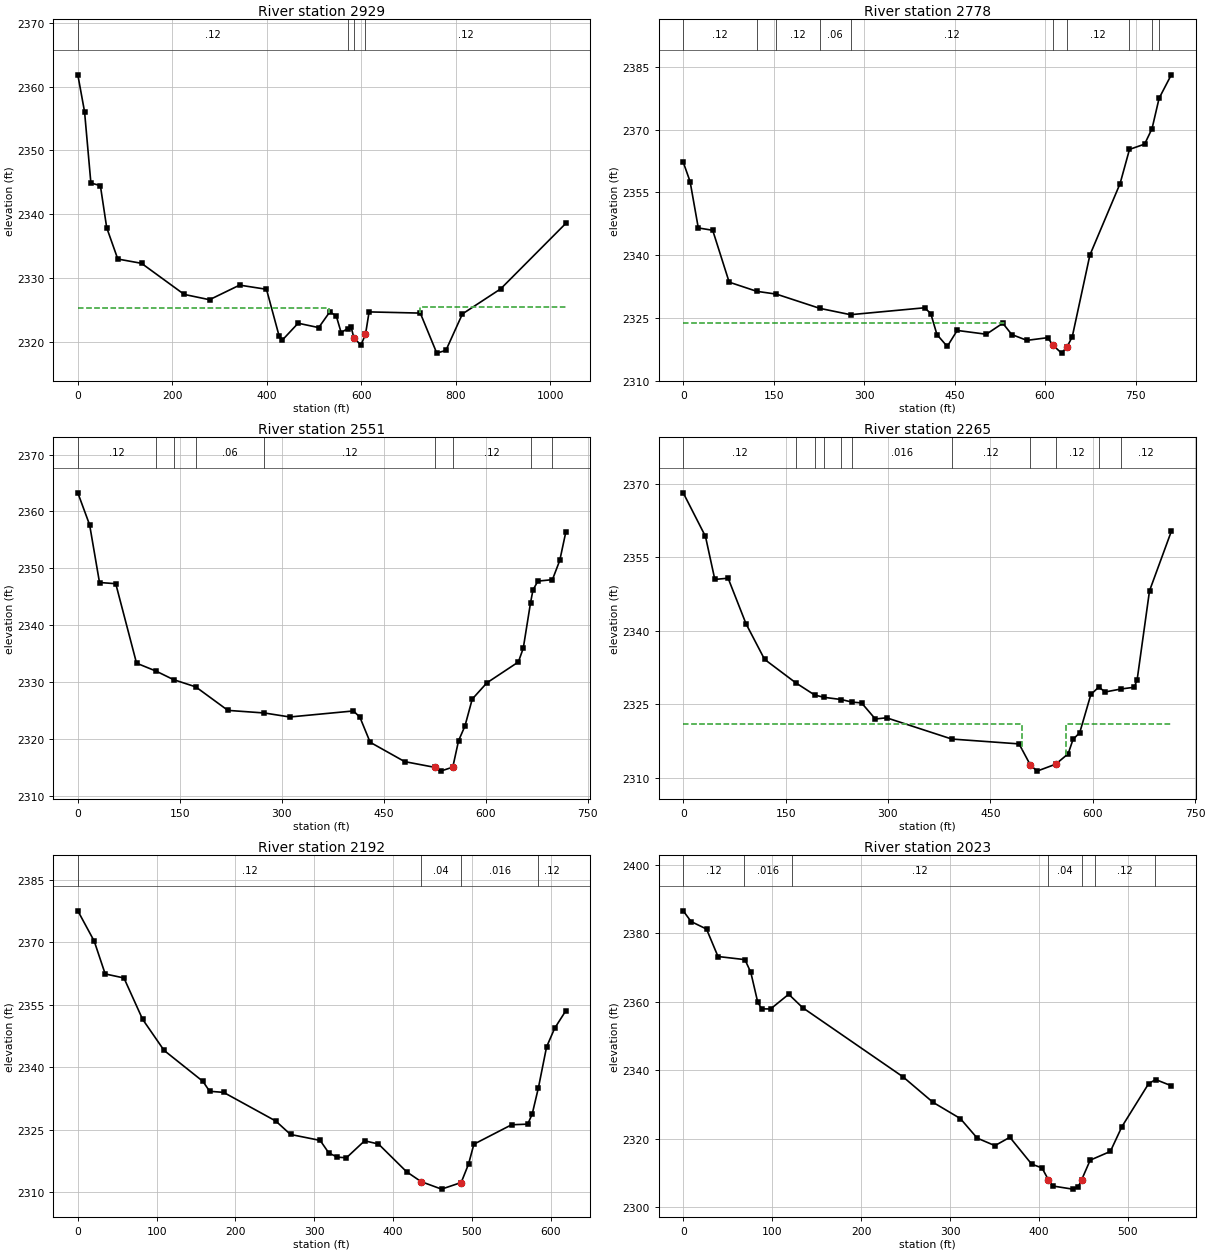
Type RM Length L Ch R = 1 ,2929    ,131.4,150.7,155.8
XS GIS Cut Line= 5
 2028344.5551881 386966.927758642028237.69989108387495.910467173
2028274.71637096387601.1397196862028391.19683246387786.793082022
 2028384.3684568387948.888108893
#Sta/Elev= 30
       02361.844  14.2552356.061  27.6432344.899  47.7262344.488  61.1142337.901
  84.5442332.992 134.751 2332.32 225.1222327.449 278.676 2326.62 342.2712328.906
 399.1722328.252 425.948 2320.92 432.6432320.292 466.1142322.939 509.6262322.252
 533.0562324.701 546.7092324.103 557.1432321.472 571.0542322.106  578.012322.415
   583.92320.683 598.8772319.506 608.6582321.197 616.2672324.711 724.6152324.524
 759.4732318.254 778.8392318.688 813.6972324.393 894.5662328.3141032.6252338.587
#Mann= 4 ,-1 , 0
       0     .12       0 571.054     .12       0   583.9    .045       0
 608.658     .12       0
#XS Ineff= 2 , 0
          531.95 2325.27  723.12         2325.54
Permanent Ineff=
       F       F
Bank Sta=583.9,608.658
XS Rating Curve= 0 ,0
Exp/Cntr(USF)=0,0
Exp/Cntr=0.3,0.1

Type RM Length L Ch R = 1 ,2778    ,216.7,227.2,229.3
XS GIS Cut Line= 3
2028328.01578072386963.3863480312028180.89191481 387480.62477155
 2028012.7973358387693.862624593
#Sta/Elev= 30
       0 2362.21    11.4 2357.58      25  2346.5    48.9 2345.94    76.2 2333.55
     122 2331.36   154.6 2330.69   226.3  2327.3   277.4 2325.78   400.2 2327.43
   410.5 2326.06   420.7 2321.04   437.8 2318.19   454.3 2322.02   502.6 2321.11
   529.9 2323.74   544.8 2321.04   569.9 2319.65   604.5 2320.29   612.82318.532
   627.3  2316.6   636.7 2318.16   645.1 2320.51   674.3 2340.01   724.4  2357.1
     740 2365.26   765.1 2366.52   777.4 2370.23   789.1 2377.47   809.3 2383.07
#Mann= 10 ,-1 , 0
       0     .12       0     122    .016       0   154.6     .12       0
   226.3     .06       0   277.4     .12       0   612.8     .04       0
   636.7     .12       0     740    .016       0   777.4     .06       0
   789.1     .12       0
#XS Ineff= 2 , 0
           531.6 2323.87
Permanent Ineff=
       F       F
Bank Sta=612.8,636.7
XS Rating Curve= 0 ,0
Exp/Cntr(USF)=0,0
Exp/Cntr=0.3,0.1

Type RM Length L Ch R = 1 ,2551    ,280.2,285.8,294
XS GIS Cut Line= 3
2028318.57810273386952.0611344412028144.92482768387318.243040521
2027858.01941673387442.820390012
#Sta/Elev= 30
       0 2363.27    17.4 2357.63    31.9 2347.52    55.8 2347.31    86.4 2333.35
   114.9 2331.97   140.8 2330.46   173.5 2329.19   220.8 2325.06   274.6  2324.6
   311.9  2323.9   405.5 2324.96     415 2323.87   430.1 2319.46   480.9 2316.06
   525.3 2315.05   533.8 2314.39   551.7 2315.09   560.2 2319.74   569.6 2322.31
   580.3 2327.04   601.8 2329.89   648.2 2333.56   655.4 2335.99   666.1 2343.97
   669.7 2346.21   676.9 2347.76   698.3 2348.02   709.1  2351.4   718.1 2356.44
#Mann= 9 ,-1 , 0
       0     .12       0   114.9     .06       0   140.8    .016       0
   173.5     .06       0   274.6     .12       0   525.3     .04       0
   551.7     .12       0   666.1    .016       0   698.3     .12       0
Bank Sta=525.3,551.7
XS Rating Curve= 0 ,0
Exp/Cntr(USF)=0,0
Exp/Cntr=0.5,0.3

Type RM Length L Ch R = 1 ,2265    ,78.7,73.4,65.1
XS GIS Cut Line= 5
2028303.47781794386931.2982428592028110.94918691387129.489480686
2027936.84749886387142.4685692862027782.07380077 387155.65348797
2027682.87255692387200.614061073
#Sta/Elev= 30
       0 2368.13    32.6 2359.23    46.3 2350.45    65.8  2350.7      92  2341.4
   119.2 2334.13   165.2 2329.31   192.7 2326.84   206.4 2326.38   231.9 2325.92
   247.5  2325.4   261.3 2325.24   281.5 2321.95   297.9  2322.2   393.5 2317.86
   492.1 2316.87   508.5 2312.59   518.4 2311.31   545.8 2312.73     564 2314.85
   571.1 2317.77     581 2319.18   597.3 2326.97   608.9 2328.47   618.2 2327.47
   641.1 2328.07   660.9 2328.44   665.1 2329.99   683.2 2348.12   715.1 2360.25
#Mann= 11 ,-1 , 0
       0     .12       0   165.2     .06       0   192.7     .12       0
   206.4    .016       0   231.9     .12       0   247.5    .016       0
   393.5     .12       0   508.5     .04       0   545.8     .12       0
   608.9    .016       0   641.1     .12       0
#XS Ineff= 2 , 0
          496.62    2321  561.04            2321
Permanent Ineff=
       F       F
Bank Sta=508.5,545.8
XS Rating Curve= 0 ,0
Exp/Cntr(USF)=0,0
Exp/Cntr=0.5,0.3

Type RM Length L Ch R = 1 ,2192    ,170.3,168.8,167.5
XS GIS Cut Line= 3
2028228.47425559386865.5747781752027903.81813268387065.653551601
2027675.42632528387131.717297543
#Sta/Elev= 30
       0 2377.58    20.8 2370.29    34.7 2362.41    58.5 2361.44    82.2  2351.5
   109.4 2344.03   158.7 2336.58   167.2  2334.2   184.9 2333.94   251.1 2327.05
   269.8 2323.82   307.4 2322.39   318.4 2319.37   329.1 2318.37   340.7 2318.21
   363.8  2322.3   381.4 2321.52     417 2314.86   435.5 2312.48   461.4 2310.68
   486.3 2312.27   495.6 2316.69   502.4 2321.48   550.2 2326.15   570.7  2326.3
   576.4 2328.75   584.3 2335.09   594.6 2344.86   604.9 2349.36   619.1 2353.58
#Mann= 4 ,-1 , 0
       0     .12       0   435.5     .04       0   486.3    .016       0
   584.3     .12       0
Bank Sta=435.5,486.3
XS Rating Curve= 0 ,0
Exp/Cntr(USF)=0,0
Exp/Cntr=0.5,0.3

Type RM Length L Ch R = 1 ,2023    ,260.8,258.3,253.7
XS GIS Cut Line= 2
2028129.82454289386719.8942558442027654.16557211386993.586917605
#Sta/Elev= 30
       0 2386.53     8.8 2383.41    26.2 2381.21    39.1  2373.2    69.4 2372.29
      76 2368.57    83.8 2359.86    88.3 2357.94    98.2 2357.89   118.6 2362.19
   134.3 2358.27   247.1  2338.1   280.8 2330.67   311.6 2325.92   330.6 2320.21
   350.5 2318.02   367.3 2320.46   391.8 2312.62   403.4 2311.52   410.6 2308.08
   415.4 2306.25   437.8 2305.33   444.1 2305.98   447.9    2308   457.6 2313.78
   480.3 2316.33   493.3 2323.56   523.3 2336.09   531.2  2337.3   548.8  2335.5
#Mann= 7 ,-1 , 0
       0     .12       0   68.44    .016       0  121.85     .12       0
   410.6     .04       0   447.9    .016       0  462.62     .12       0
  530.78    .016       0
Bank Sta=410.6,447.9
XS Rating Curve= 0 ,0
Exp/Cntr(USF)=0,0
Exp/Cntr=0.3,0.1

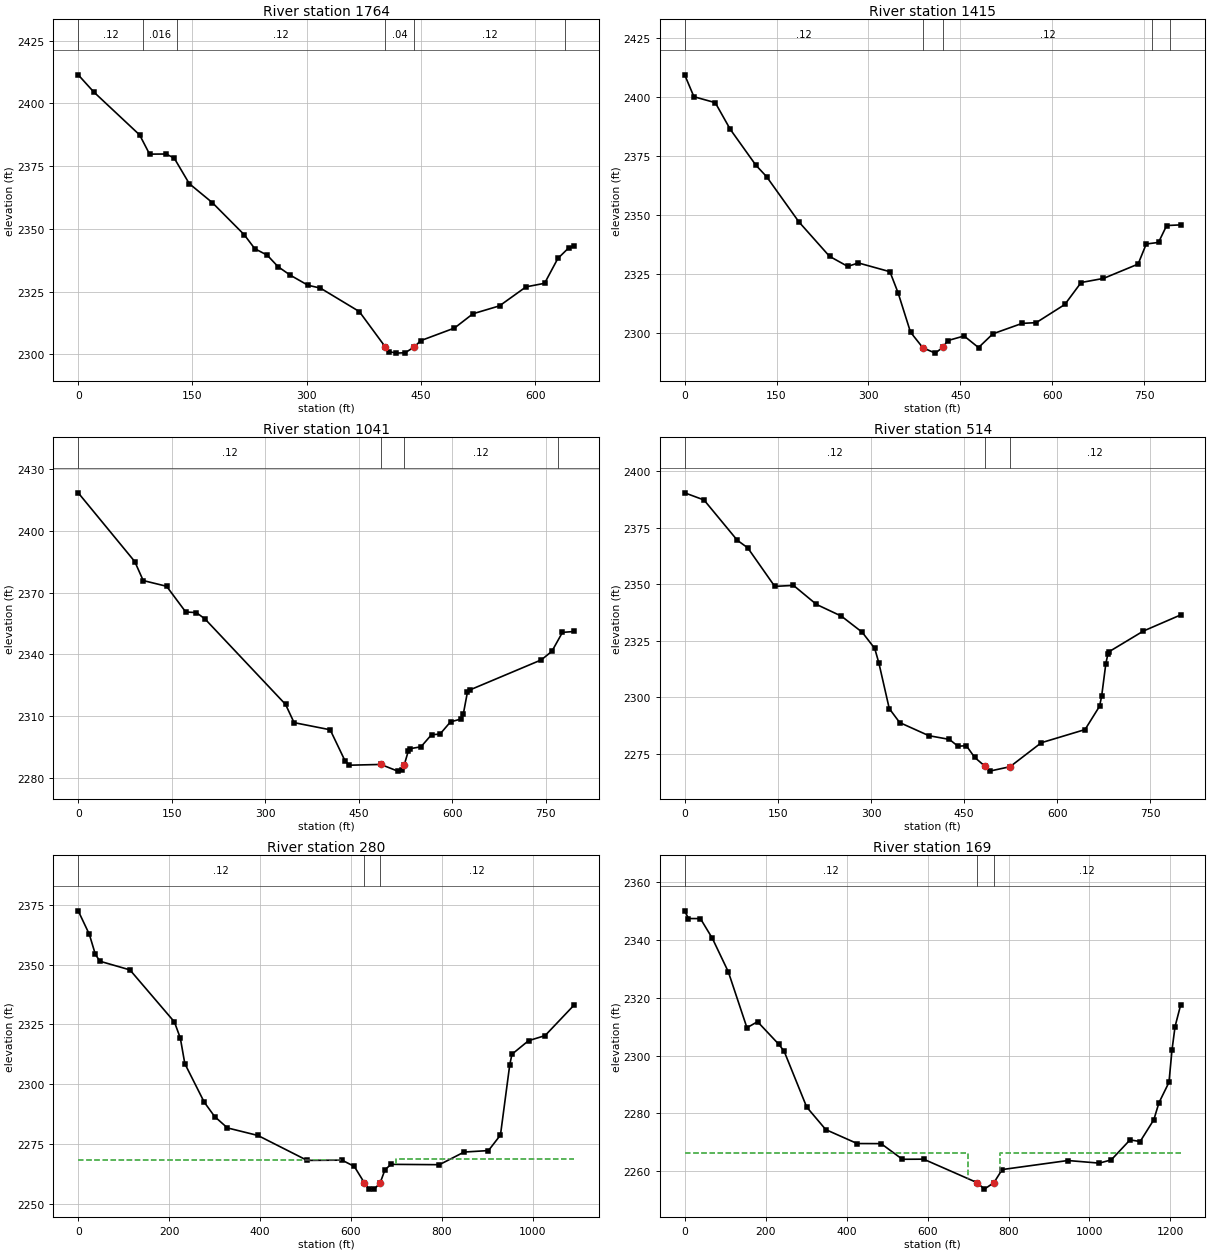
Type RM Length L Ch R = 1 ,1764    ,361.6,349.9,340.4
XS GIS Cut Line= 4
2027950.50866105386432.9888448952027697.57889087386650.055438705
2027589.98936177386753.8698966142027533.36329381386912.422886876
#Sta/Elev= 30
       0 2411.42    20.2 2404.65    80.7 2387.44    93.7  2379.8   115.3 2379.85
     126 2378.24   145.8 2368.04   176.1 2360.46     218 2347.66   231.9 2342.08
   248.2 2339.52   262.3 2334.95   278.4 2331.55   301.7 2327.52     318 2326.39
   369.1 2317.03   403.4 2302.86   408.5 2301.04   417.6 2300.46   429.4 2300.62
   440.8 2302.83   449.9 2305.45     494 2310.45   518.3 2316.15   553.2 2319.31
     588 2326.88   612.4  2328.3   629.8 2338.21   644.5 2342.56   651.2 2343.13
#Mann= 6 ,-1 , 0
       0     .12       0   84.76    .016       0  130.12     .12       0
   403.4     .04       0   440.8     .12       0   639.8    .016       0
Bank Sta=403.4,440.8
XS Rating Curve= 0 ,0
Exp/Cntr(USF)=0,0
Exp/Cntr=0.3,0.1

Type RM Length L Ch R = 1 ,1415    ,374.9,373.5,373.2
XS GIS Cut Line= 4
2027248.34541846386136.6457559532027354.04741197386431.101309296
2027414.44855112386699.1313642622027450.31172749386918.085493671
#Sta/Elev= 30
       0 2409.23    15.1 2399.97    49.9 2397.46    74.4 2386.19   116.2 2371.02
   133.6  2366.2   186.4 2347.05   236.4 2332.49   266.1 2328.23   283.5 2329.68
     335 2325.98   348.4 2317.01   368.6 2300.42   388.8 2293.81     409 2291.55
   421.8 2294.08   429.1 2296.83   456.1  2298.8   479.6  2293.9   503.1 2299.72
   550.8 2304.13   573.8 2304.44   620.5 2312.12   647.1 2321.41   683.6 2323.14
   740.1  2329.2   753.4  2337.7   773.4 2338.36   786.7  2345.5   809.5 2345.78
#Mann= 5 ,-1 , 0
       0     .12       0   388.8     .04       0   421.8     .12       0
  762.95    .016       0  792.88     .12       0
Bank Sta=388.8,421.8
XS Rating Curve= 0 ,0
Exp/Cntr(USF)=0,0
Exp/Cntr=0.3,0.1

Type RM Length L Ch R = 1 ,1041    ,528.5,527.3,526.8
XS GIS Cut Line= 3
2026919.91422435386217.8097866832027029.39128905386604.754584344
2027127.54314017386986.036775211
#Sta/Elev= 30
       0 2418.52    90.7  2385.1   104.3 2375.85   141.8 2373.07   172.5 2360.57
   189.5 2360.27   203.2 2357.25   332.7 2315.61   346.4 2306.74   404.3 2303.28
     428 2288.25   434.8 2286.04   485.6 2286.41   512.7 2283.16   519.5 2283.78
  523.25 2286.31   529.7 2292.95   533.1 2294.11     550 2294.99   566.9 2300.87
   580.5 2301.16   597.4 2307.12   614.4 2308.51   617.8 2310.73   624.5 2321.48
   627.9 2322.58   743.1 2337.27   760.1 2341.46     777 2350.64   795.8 2351.08
#Mann= 4 ,-1 , 0
       0     .12       0   485.6     .04       0  523.25     .12       0
  769.77    .016       0
Bank Sta=485.6,523.25
XS Rating Curve= 0 ,0
Exp/Cntr(USF)=0,0
Exp/Cntr=0.3,0.1

Type RM Length L Ch R = 1 ,514     ,234.6,234,233.5
XS GIS Cut Line= 2
2026440.48018237386238.5726782642026604.69577943387020.012415982
#Sta/Elev= 30
       0 2390.34    31.1 2387.18    84.7 2369.36   101.5 2366.01     145 2348.96
   175.2 2349.39   212.1 2340.99   252.3  2335.8   285.8 2328.68     306  2321.5
   312.7 2315.02   329.4  2294.9   346.2 2288.72   393.1 2282.92   426.2 2281.28
     440 2278.25   453.5 2278.49   466.9 2273.32   483.6 2269.37     491 2267.24
   523.9  2269.2   574.2  2279.8   644.6 2285.62     668 2295.94   671.4  2300.5
   678.1 2314.79   681.4 2319.04   683.8 2320.15   738.4 2329.18   798.5 2336.32
#Mann= 3 , 0 , 0
       0     .12       0   483.6     .04       0   523.9     .12       0
Bank Sta=483.6,523.9
XS Rating Curve= 0 ,0
Exp/Cntr(USF)=0,0
Exp/Cntr=0.3,0.1

Type RM Length L Ch R = 1 ,280     ,110.7,111,110.9
XS GIS Cut Line= 4
2026316.67384269386149.361088734 2026293.6586243386693.095623239
2026339.68906109386874.3404680742026495.04178523387199.430427857
#Sta/Elev= 30
       0 2372.48    24.5 2362.63    37.6 2354.33    47.7 2351.39   113.8 2347.77
   211.7 2325.99   224.8 2319.18   234.6 2308.56   277.3 2292.44   300.3  2286.4
   328.4 2281.65   395.5 2278.49   503.9 2268.06   580.5 2268.17   607.6 2265.54
  629.82 2258.66   638.9 2256.19   651.6 2256.04  664.58 2258.66   675.3 2264.23
   688.8 2266.41   794.8 2266.26   849.3 2271.55   902.9 2272.17   929.3 2278.66
   949.7 2307.99   954.6 2312.48   991.1 2318.15  1027.5 2320.27  1091.5 2333.08
#Mann= 3 , 0 , 0
       0     .12       0  629.82     .04       0  664.58     .12       0
#XS Ineff= 2 , 0
          578.73 2268.27  698.74         2268.48
Permanent Ineff=
       F       F
Bank Sta=629.82,664.58
XS Rating Curve= 0 ,0
Exp/Cntr(USF)=0,0
Exp/Cntr=0.3,0.1

Type RM Length L Ch R = 1 ,169     ,19.6,19.6,19.6
XS GIS Cut Line= 4
2026204.53823258386085.6822947982026191.32548339386734.994540631
2026230.96373095386899.2101376872026391.40425681387272.942186161
#Sta/Elev= 30
       0 2350.18     9.4 2347.51    38.9 2347.49    68.5 2340.61   107.8 2329.05
   153.8 2309.68     180 2311.77   232.5 2303.94   245.7 2301.53   301.4  2282.2
   348.5 2274.39   426.1 2269.56   485.2 2269.53   537.7 2264.11   590.2 2264.15
  722.59    2256   740.4 2253.77     764 2256.03   784.3 2260.55   946.6 2263.68
  1024.1 2262.78  1053.7 2263.89  1100.1 2270.83  1125.1 2270.26    1159 2277.83
  1171.5 2283.67  1196.3 2290.76  1203.9 2302.07  1211.4  2310.1  1225.1 2317.53
#Mann= 3 , 0 , 0
       0     .12       0  722.59     .04       0     764     .12       0
#XS Ineff= 2 , 0
          700.12 2266.34  779.85         2266.38
Permanent Ineff=
       F       F
Bank Sta=722.59,764
XS Rating Curve= 0 ,0
Exp/Cntr(USF)=0,0
Exp/Cntr=0.3,0.1
LCMann Table=0

Chan Stop Cuts=-1
Use User Specified Reach Order=0
Composite Channel Slope=5